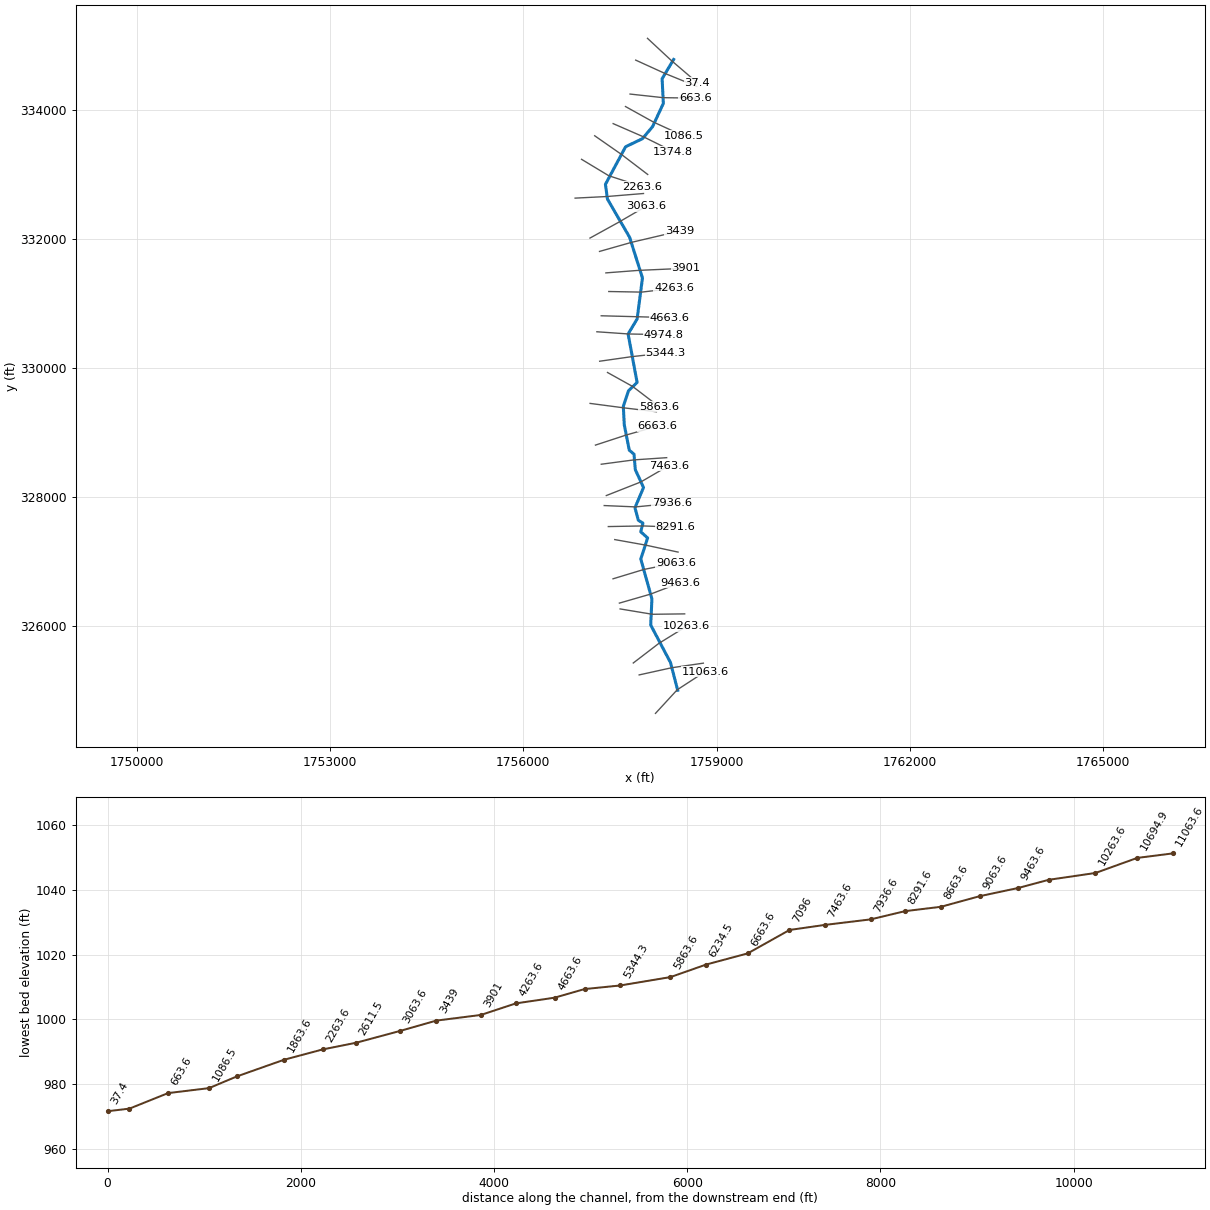
--- CoonsRn.prj (project) ---

Proj Title=CoonsRn
Current Plan=p01
Default Exp/Contr=0,0
English Units
Geom File=g01
Flow File=f01
Plan File=p01
BEGIN DESCRIPTION:
END DESCRIPTION:
DSS Export Rating Curves= 0
DSS Export Rating Curve Sorted= 0
DSS Export Volume Flow Curves= 0
DXF OffsetX= 0
DXF OffsetY= 0
DXF ScaleX= 0
DXF ScaleY= 0

--- CoonsRn.p01 (plan) ---

Plan Title=Floodplain
Program Version=4.00
Geom File=g01
Flow File=f01
K Sum by GR=0
Std Step Tol=0.01
Critical Tol=0.01
Num of Std Step Trials=20
Max Error Tol=0.3
Flow Tol Ratio=0.001
Split Flow NTrial=30
Split Flow Tol=0.02
Split Flow Ratio=0.02
Log Output Level=0
Friction Slope Method=1
Unsteady Friction Slope Method=2
Unsteady Bridges Friction Slope Method=1
Global Log Level=0
CheckData=False
Run HTab=0
Run UNet=0
Run PostProcess=0
UNET Theta=0
UNET Theta Warmup=0
UNET ZTol=0
UNET ZSATol=0
UNET MxIter=0
UNET MaxInSteps=0
UNET DtIC=0
UNET DtMin=0
UNET MaxCRTS=0
UNET WFStab=0
UNET SFStab=0
UNET WFX=0
UNET SFX=0
UNET DSS MLevel=0
UNET DZMax Abort=0
UNET Convert EG Bridges=0
UNET Use Existing IB Tables=0
UNET Froude Limit=0
UNET Froude Power=0
Write IC File=0
Echo Input=False
Echo Output=False
Write Detailed=0

--- CoonsRn.f01 (steady flow) ---

Flow Title=NFF Regression Equation
Program Version=4.00
Number of Profiles=1
Profile Names=P100yr
River Rch & RM=CoonsRn,Main      ,11063.6
780.4385
River Rch & RM=CoonsRn,Main      ,8663.6
859.0876
River Rch & RM=CoonsRn,Main      ,8291.6
965.1096
River Rch & RM=CoonsRn,Main      ,7096
1066.985
River Rch & RM=CoonsRn,Main      ,4974.8
1174.942
River Rch & RM=CoonsRn,Main      ,3063.6
1305.332
River Rch & RM=CoonsRn,Main      ,263.6
1432.737
River Rch & RM=CoonsRn,Main      ,37.4
1438.099
Boundary for River Rch & Prof#=CoonsRn,Main      ,1
Up Type=0
Dn Type=3
Dn Slope=0.007429

--- CoonsRn.g01 (geometry) ---

Geom Title=USGS 3m DEM
Program Version=4.00

River Reach=CoonsRn         ,Main
Reach XY= 30
     1758397.363      325009.892     1758285.955       325439.49
     1757978.747      326021.865     1757997.841      326425.225
     1757824.976      327045.056     1757931.068      327370.321
     1757824.261      327467.177     1757858.315      327600.564
     1757787.042      327644.991     1757734.646      327838.461
     1757867.341      328152.881     1757740.067      328430.001
     1757719.529       328670.17     1757646.246      328731.355
     1757569.003      329124.411     1757553.899      329410.542
     1757634.501      329653.335     1757767.935      329781.477
       1757628.4      330532.512     1757768.153      330765.799
     1757851.149      331402.022     1757651.645      332032.649
     1757307.934      332624.661     1757276.376      332853.757
     1757589.589      333436.461     1757850.563      333560.928
      1758008.33      333748.762     1758175.049      334108.139
      1758155.89      334490.718     1758334.966       334789.96

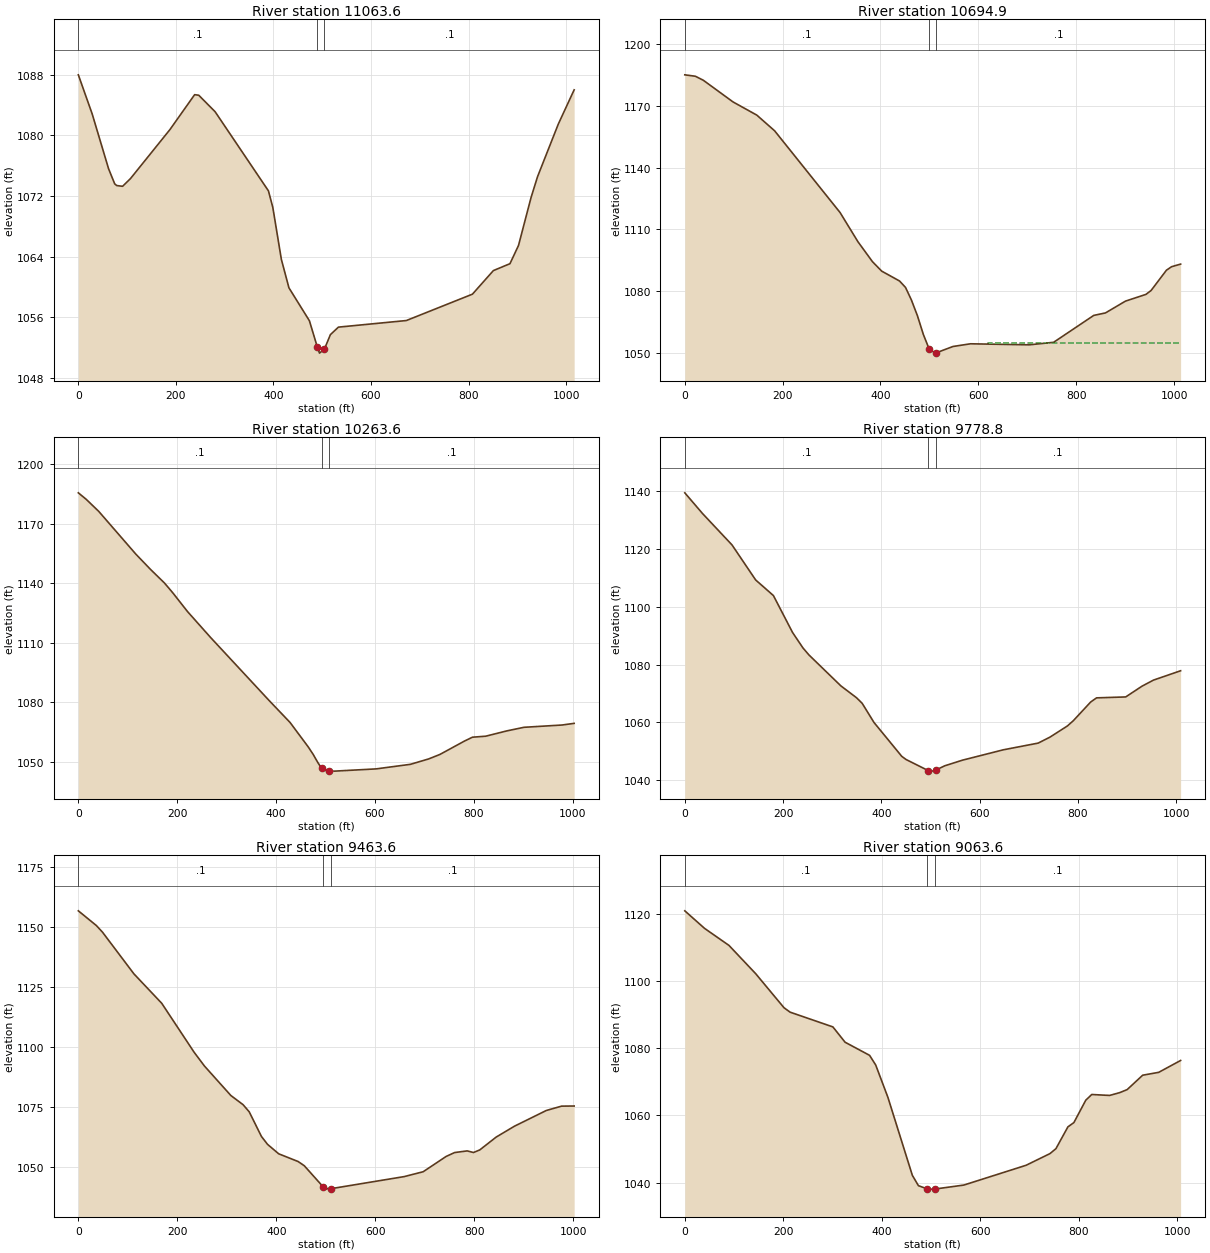
Type RM Length L Ch R = 1 ,11063.6 ,382.628,368.635,359.326
XS GIS Cut Line= 3
     1758053.169      324651.148      1758390.01      325016.669
     1758826.054      325299.984
#Sta/Elev= 30
       0    1088    28.4 1082.84      62 1075.61    74.6 1073.61    78.8 1073.39
    90.7 1073.29   106.9 1074.31   187.6 1080.76   238.4 1085.38   246.8 1085.31
   280.4 1083.13   389.7 1072.69   398.7  1070.5   416.2 1063.65   431.7  1059.9
   473.7 1055.55   489.6 1052.15   494.4 1051.28   504.6 1051.83   516.7 1053.72
   533.2 1054.71   672.4 1055.58   807.9 1059.06   850.8 1062.17   884.8 1063.08
   902.3 1065.48     928  1071.8   941.4 1074.57   983.9  1081.5  1016.4 1086.02
#Mann= 3 , 0 , 0
       0      .1       0   489.6    .045       0   504.6      .1       0
Bank Sta=489.6,504.6
XS Rating Curve= 0 ,0
Exp/Cntr=0.3,0.1

Type RM Length L Ch R = 1 ,10694.9 ,421.503,431.365,439.989
XS GIS Cut Line= 3
     1757799.642      325247.477     1758303.223      325358.453
     1758795.908      325429.794
#Sta/Elev= 30
       0 1185.21    21.6 1184.52    37.8 1182.58    98.6 1172.03   147.2 1165.62
   183.7 1157.97   317.4 1118.24   353.9 1104.06   383.6 1094.35   402.5 1089.75
     439 1084.95   451.2 1081.82   463.3 1075.67   475.5 1068.08   487.6 1058.98
   499.4 1051.93   511.9 1049.88   514.4 1050.07     548  1053.1     584 1054.42
   703.9 1053.91   753.9 1055.14   835.9 1068.22   859.9 1069.43   900.7 1075.16
   942.6 1078.45   953.1 1080.33   984.5  1090.2     995  1091.9  1013.5 1093.17
#Mann= 3 , 0 , 0
       0      .1       0   499.4    .045       0   514.4      .1       0
#XS Ineff= 2 , 0
                          619.94         1054.76
Permanent Ineff=
       F       F
Bank Sta=499.4,514.4
XS Rating Curve= 0 ,0
Exp/Cntr=0.3,0.1

Type RM Length L Ch R = 1 ,10263.6 ,503.313,484.8,471.717
XS GIS Cut Line= 3
     1757708.721      325432.455     1758105.817      325736.437
     1758534.139      325999.979
#Sta/Elev= 30
       0  1185.5    15.9 1182.24    41.4 1176.12   116.1 1154.67     146 1146.91
   174.3 1140.03   190.9 1135.16   220.8 1125.68   267.4 1112.63     386 1080.81
   428.4 1069.73   465.1 1057.43     475 1053.69   484.6 1049.52   489.9 1047.48
   492.6 1046.76   496.1 1045.83   507.6 1045.25   518.5 1045.23   602.1 1046.35
   671.8 1048.66   708.7 1051.38   731.4 1053.63   780.8 1060.34   797.3 1062.33
     824 1062.83     867 1065.52   901.6 1067.32   978.5 1068.47    1003 1069.31
#Mann= 3 , 0 , 0
       0      .1       0   492.6    .045       0   507.6      .1       0
Bank Sta=492.6,507.6
XS Rating Curve= 0 ,0
Exp/Cntr=0.3,0.1

Type RM Length L Ch R = 1 ,9778.8  ,305.157,315.2,324.029
XS GIS Cut Line= 3
     1757504.331      326270.606     1758005.246      326187.498
      1758506.27       326193.74
#Sta/Elev= 30
       0 1139.44    35.9 1132.31    96.1  1121.4   144.2 1109.28   180.3 1103.88
   219.3 1091.09   240.5 1085.73   252.5 1083.34   317.6 1072.61   349.2 1068.54
   360.8 1066.61   384.9 1059.96   441.4 1048.23   450.2 1047.13   495.3  1043.3
   505.3 1043.11   510.3 1043.45     529 1044.96   564.7 1046.89   647.8 1050.48
     719 1052.81   743.1 1054.89   778.4 1058.74   790.3 1060.53   825.9 1067.05
   837.8 1068.47   897.1 1068.79   930.1  1072.5   953.5 1074.61  1008.8 1077.85
#Mann= 3 , 0 , 0
       0      .1       0   495.3    .045       0   510.3      .1       0
Bank Sta=495.3,510.3
XS Rating Curve= 0 ,0
Exp/Cntr=0.3,0.1

Type RM Length L Ch R = 1 ,9463.6  ,399.732,400,396.164
XS GIS Cut Line= 3
     1757492.901      326360.794     1757975.797      326499.924
     1758442.893      326678.702
#Sta/Elev= 30
       0 1156.85    36.4 1150.71    48.7 1147.97   112.4  1130.5   168.5 1118.23
   234.1 1097.73   254.8 1092.02   308.2  1079.7   332.9 1075.86   345.3 1072.88
     370 1062.58   382.3 1059.29   404.8 1055.35   444.1 1052.12   456.5 1050.37
     495 1041.47     506 1040.59     510 1040.76   658.6 1045.83   696.7 1047.85
   743.2 1054.25   760.3 1055.87   785.7 1056.56   798.4 1055.89   811.1 1056.97
   844.3 1062.34   881.1 1066.87   945.4 1073.43   976.4 1075.26  1001.8 1075.31
#Mann= 3 , 0 , 0
       0      .1       0     495    .045       0     510      .1       0
Bank Sta=495,510
XS Rating Curve= 0 ,0
Exp/Cntr=0.3,0.1

Type RM Length L Ch R = 1 ,9063.6  ,410.636,400,390.771
XS GIS Cut Line= 3
     1757394.485      326737.683     1757872.921      326882.564
     1758369.624      326982.456
#Sta/Elev= 30
       0 1120.83    40.1 1115.61    89.7 1110.54   143.9 1102.13   201.4    1092
   213.8 1090.68   300.6  1086.3   325.4 1081.74   375.1 1077.84   387.5 1074.98
   412.3 1065.35   461.9 1042.15   474.3 1039.06   492.4  1038.1   499.1 1038.04
   507.4 1038.06   566.5 1039.25   692.9 1045.14   741.3 1048.61   753.4 1050.08
   777.7 1056.56   789.8 1057.83     814  1064.5   826.1 1066.19   862.4 1065.91
   882.9 1066.75     898 1067.65   929.5 1071.93     962 1072.78  1006.5 1076.31
#Mann= 3 , 0 , 0
       0      .1       0   492.4    .045       0   507.4      .1       0
Bank Sta=492.4,507.4
XS Rating Curve= 0 ,0
Exp/Cntr=0.3,0.1

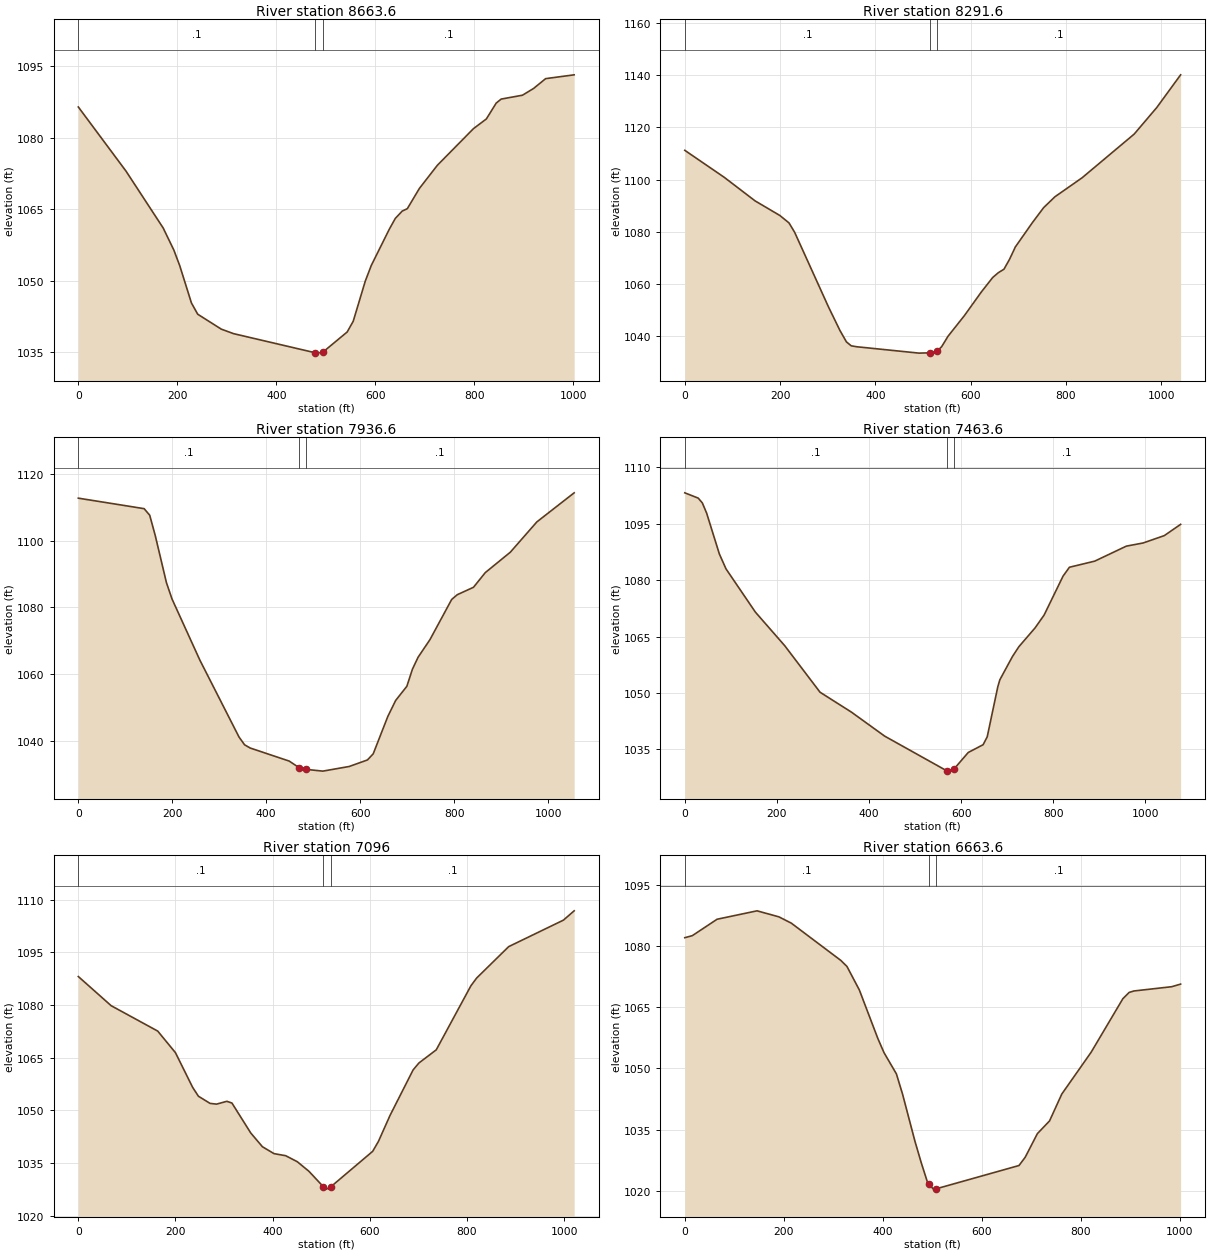
Type RM Length L Ch R = 1 ,8663.6  ,362.687,371.996,376.244
XS GIS Cut Line= 3
     1757421.114      327345.645     1757899.737      327260.019
     1758403.422      327151.803
#Sta/Elev= 30
       0 1086.44    96.4 1072.96   171.3 1061.05   192.9 1056.41   204.9  1053.1
   228.4 1045.31   241.1 1042.94   288.8  1039.8   313.5 1038.86   478.7 1034.84
   482.3 1034.77   493.7 1034.96     543 1039.21   555.2 1041.47   579.5 1049.87
   591.6 1053.16     628 1060.77   640.2 1063.05   654.1 1064.58   664.5  1065.1
   688.8 1069.34   725.2 1074.21   798.1  1081.9   824.1 1083.93     844 1087.26
     854  1088.1     897 1088.91   919.5 1090.33   943.8 1092.39  1001.4 1093.19
#Mann= 3 , 0 , 0
       0      .1       0   478.7    .045       0   493.7      .1       0
Bank Sta=478.7,493.7
XS Rating Curve= 0 ,0
Exp/Cntr=0.3,0.1

Type RM Length L Ch R = 1 ,8291.6  ,354.332,354.942,355.619
XS GIS Cut Line= 3
      1757321.06      327547.403     1757862.526      327557.284
     1758361.344      327537.899
#Sta/Elev= 30
       0 1111.23    82.7 1100.89   147.5 1091.84   199.4 1086.25   218.7 1083.39
   230.6 1079.78   301.8 1051.08   325.6 1042.14   339.3 1037.73   349.3 1036.23
   361.2 1035.86   491.8 1033.42   514.2 1033.54   529.2 1034.05   539.3 1035.93
   552.6 1039.91   586.9 1047.81   622.5 1056.89   646.3 1062.43   658.1 1064.28
     670 1065.62   681.9  1069.5   693.8 1074.14   729.4 1083.43   753.2 1089.23
     777 1093.42     834  1100.7   943.3 1117.46   990.8 1127.67  1040.8  1140.2
#Mann= 3 , 0 , 0
       0      .1       0   514.2    .045       0   529.2      .1       0
Bank Sta=514.2,529.2
XS Rating Curve= 0 ,0
Exp/Cntr=0.3,0.1

Type RM Length L Ch R = 1 ,7936.6  ,456.991,473.061,479.045
XS GIS Cut Line= 3
     1757257.324      327873.192     1757745.959      327852.247
     1758309.799      327907.473
#Sta/Elev= 30
       0 1112.75   140.1  1109.6     152 1107.62   163.8 1101.52   187.6  1087.4
   199.5  1082.5   258.9 1064.13   342.1 1041.11     354 1038.77   365.9 1037.81
     449 1033.89   470.4 1031.88   485.4  1031.4   520.5 1030.88   576.8 1032.28
   615.5 1034.23   627.8 1036.07   658.9 1047.28   675.6 1052.08   699.4 1056.32
   711.3 1061.46   723.3 1065.03   748.7 1070.34   794.8 1082.36   806.8  1083.8
   841.3 1086.02   866.4 1090.42   919.7 1096.54   976.2 1105.63  1055.6 1114.35
#Mann= 3 , 0 , 0
       0      .1       0   470.4    .045       0   485.4      .1       0
Bank Sta=470.4,485.4
XS Rating Curve= 0 ,0
Exp/Cntr=0.3,0.1

Type RM Length L Ch R = 1 ,7463.6  ,373.05,367.544,357.199
XS GIS Cut Line= 3
     1757290.269      328028.239     1757826.593      328239.626
     1758258.996      328491.065
#Sta/Elev= 30
       0 1103.24    29.2 1101.83    38.1 1100.55    47.5 1097.81      75 1086.99
    89.5    1083   153.3 1071.49   217.1 1062.54   293.7 1050.17   361.9 1044.87
   434.1 1038.48     569 1029.25   578.3 1029.17     584 1029.65   615.5 1034.13
   647.8  1036.2   656.7 1038.29   679.7 1051.62   684.1 1053.47   711.6 1059.69
   725.3 1062.26   760.7  1067.3   780.3 1070.72   821.4 1081.07   835.2 1083.43
   890.2 1085.06   958.8 1089.05   995.2 1089.89  1041.2 1091.85  1076.7 1094.85
#Mann= 3 , 0 , 0
       0      .1       0     569    .045       0     584      .1       0
Bank Sta=569,584
XS Rating Curve= 0 ,0
Exp/Cntr=0.3,0.1

Type RM Length L Ch R = 1 ,7096    ,427.897,432.456,437.248
XS GIS Cut Line= 3
     1757211.555      328513.937     1757719.868      328581.404
      1758226.62      328615.597
#Sta/Elev= 30
       0  1088.1    67.6  1079.8   163.4 1072.58   199.9 1066.44   235.3 1056.57
   247.2 1054.04   271.2    1052   284.5 1051.79   305.7 1052.59   316.2  1052.1
     355 1043.57     379 1039.66   402.9  1037.7   426.9 1037.11   450.8  1035.4
   474.7 1032.68   504.3  1028.3   510.7  1027.6   519.3 1028.21   605.9 1038.35
   617.8 1041.18   641.6 1048.56   689.2 1061.53   701.1 1063.49   736.8 1067.24
   808.2 1085.48   820.1 1087.69   885.9 1096.61   998.6 1104.15  1020.7  1106.8
#Mann= 3 , 0 , 0
       0      .1       0   504.3    .045       0   519.3      .1       0
Bank Sta=504.3,519.3
XS Rating Curve= 0 ,0
Exp/Cntr=0.3,0.1

Type RM Length L Ch R = 1 ,6663.6  ,439.128,429.026,420.064
XS GIS Cut Line= 3
     1757121.582      328810.488     1757597.099      328966.185
     1758079.328       329103.17
#Sta/Elev= 30
       0 1082.13    15.2 1082.63    65.2 1086.66     146 1088.73   190.1 1087.25
   215.1 1085.71   315.1 1076.56   327.6 1075.07   352.6  1069.3     390 1057.37
   402.5 1053.88   427.5 1048.67     440 1043.67     465 1032.11   477.5 1026.92
     490 1022.16   492.9 1021.55   502.4 1020.36   507.9 1020.44   675.2 1026.16
   687.6 1028.17   712.3 1033.99   736.9 1037.12   761.6 1043.71   820.9 1053.99
   885.1 1067.16   897.8 1068.69   907.4 1069.04   983.8 1070.09  1001.7 1070.73
#Mann= 3 , 0 , 0
       0      .1       0   492.9    .045       0   507.9      .1       0
Bank Sta=492.9,507.9
XS Rating Curve= 0 ,0
Exp/Cntr=0.3,0.1

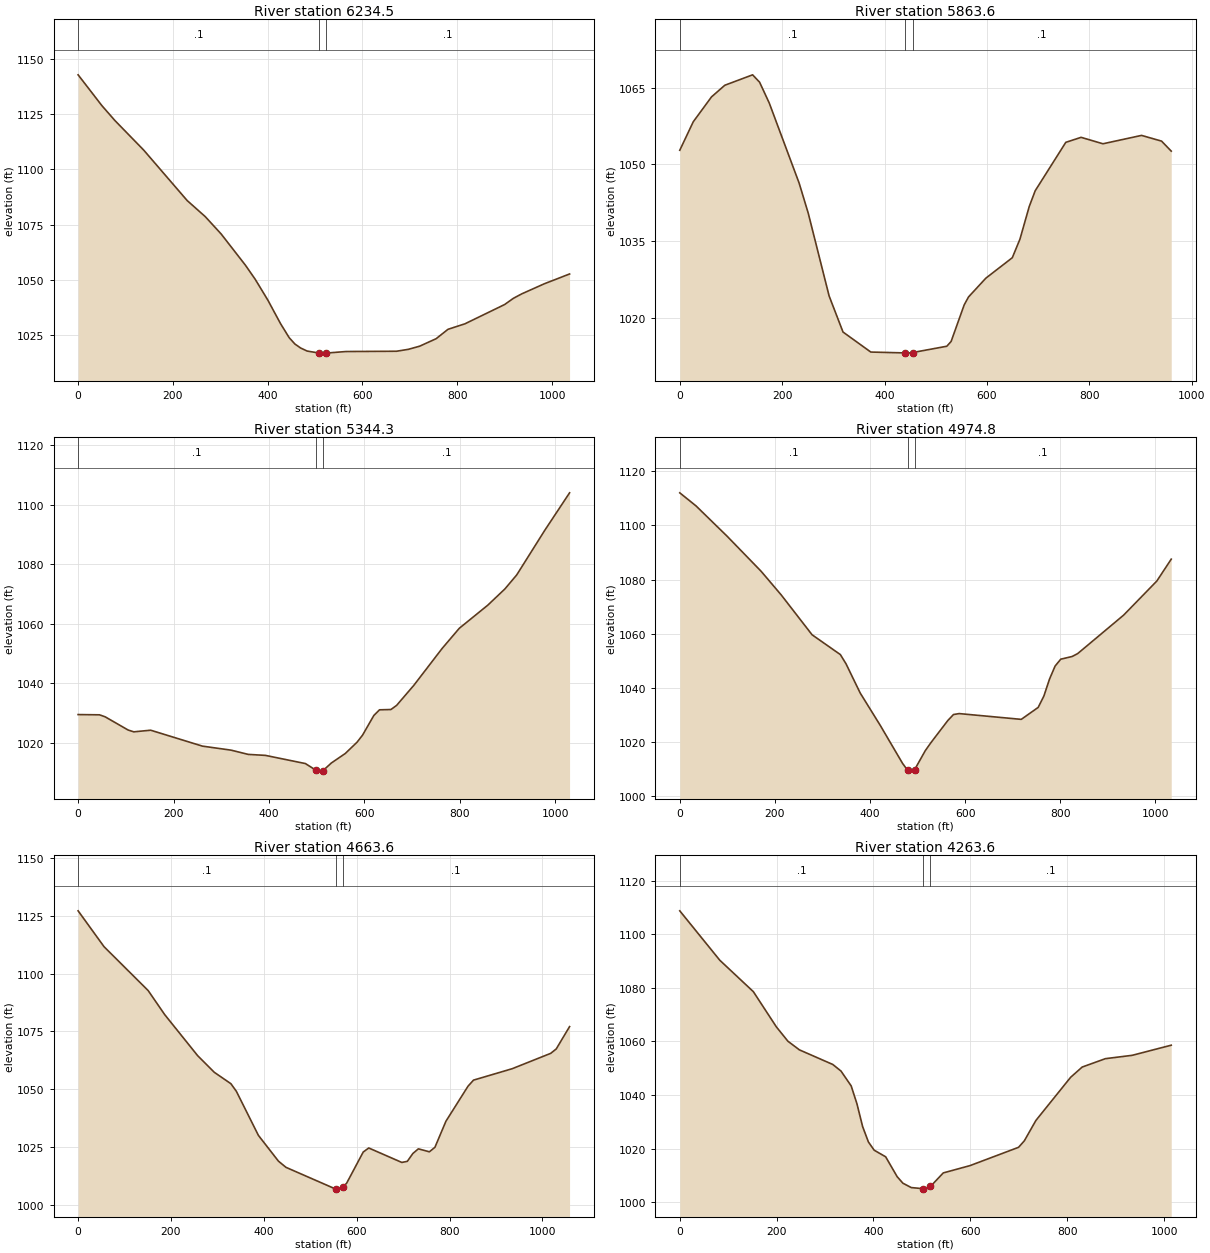
Type RM Length L Ch R = 1 ,6234.5  ,379.04,370.974,359.034
XS GIS Cut Line= 3
     1757038.669      329456.953      1757549.26      329389.769
     1758067.544      329327.576
#Sta/Elev= 30
       0 1142.73    50.3 1128.77    77.9 1122.01   138.5 1108.68     230 1085.92
   268.4  1078.6   301.8 1070.79   353.1 1056.65   373.7  1050.3   400.5 1040.83
   427.2 1030.22   445.5 1023.87   457.5 1021.03   469.5 1019.24   483.2 1017.86
   508.4 1016.96   517.4 1016.92   523.4 1016.94     565 1017.64   671.9 1017.77
   696.7 1018.63   720.6 1020.05   755.5 1023.45   780.4 1027.68   816.3 1030.18
     900 1038.89   918.5  1041.7   935.9 1043.69   983.7 1048.27    1037  1052.7
#Mann= 3 , 0 , 0
       0      .1       0   508.4    .045       0   523.4      .1       0
Bank Sta=508.4,523.4
XS Rating Curve= 0 ,0
Exp/Cntr=0.3,0.1

Type RM Length L Ch R = 1 ,5863.6  ,504.536,519.303,538.154
XS GIS Cut Line= 3
     1757308.476      329936.319     1757699.512      329719.134
     1758107.111      329407.997
#Sta/Elev= 30
       0 1052.75    26.3 1058.32      62  1063.2      88 1065.48   142.3 1067.52
   155.9 1066.08   174.8    1062   233.2 1046.31     251 1040.42   291.7 1024.24
   318.9 1017.16   373.2 1013.24   439.8 1013.07   445.4 1013.03   454.8 1013.14
   521.7 1014.38   530.1 1015.32   555.6 1022.47   564.1 1024.03     598 1027.71
   649.6 1031.71   664.5 1035.33   682.7 1041.74   694.4 1044.83   754.1  1054.3
     784 1055.28   826.7 1054.02   902.1 1055.66   941.2 1054.54   960.1 1052.58
#Mann= 3 , 0 , 0
       0      .1       0   439.8    .045       0   454.8      .1       0
Bank Sta=439.8,454.8
XS Rating Curve= 0 ,0
Exp/Cntr=0.3,0.1

Type RM Length L Ch R = 1 ,5344.3  ,374.038,369.51,366.2
XS GIS Cut Line= 3
     1757186.713      330110.916      1757680.15      330181.147
     1758208.762      330239.934
#Sta/Elev= 30
       0 1029.44    44.8 1029.36    56.8 1028.68   104.7 1024.26   116.7 1023.64
   152.1 1024.19   260.6 1018.84   320.6 1017.49   356.6 1016.06   392.6 1015.73
   476.5 1012.98   498.6 1010.74   512.4 1010.44   513.6 1010.64   530.8 1013.16
   560.2 1016.38   584.6 1020.13   596.1 1022.48   619.9 1029.12   631.9 1031.04
   655.8 1031.14   667.7 1032.53   703.6 1039.23   763.3 1051.69   799.1 1058.43
   858.9 1066.21   894.7 1071.65   919.5 1076.37   978.3 1091.35  1030.3 1103.95
#Mann= 3 , 0 , 0
       0      .1       0   498.6    .045       0   513.6      .1       0
Bank Sta=498.6,513.6
XS Rating Curve= 0 ,0
Exp/Cntr=0.3,0.1

Type RM Length L Ch R = 1 ,4974.8  ,310.185,311.187,311.38
XS GIS Cut Line= 3
     1757143.449      330567.616     1757636.281      330533.385
     1758175.625      330523.119
#Sta/Elev= 30
       0 1111.97    34.2 1107.14    99.7 1095.94   171.1 1083.03   213.2 1074.34
   278.2 1059.62   337.7 1052.31   349.6 1048.91   379.5 1038.11   421.1 1026.35
   468.4 1012.22   478.9  1009.7   480.6 1009.33   493.9 1009.88   516.2 1016.86
   528.1 1019.82   563.7    1028   575.6  1030.2   587.5 1030.55   718.1 1028.42
   753.7 1032.83   765.6 1036.99   777.5 1043.26   789.3 1048.09   801.2 1050.62
     825  1051.6   836.8 1052.68   933.3 1066.85  1003.2 1079.44  1033.5 1087.51
#Mann= 3 , 0 , 0
       0      .1       0   478.9    .045       0   493.9      .1       0
Bank Sta=478.9,493.9
XS Rating Curve= 0 ,0
Exp/Cntr=0.3,0.1

Type RM Length L Ch R = 1 ,4663.6  ,399.533,400,403.648
XS GIS Cut Line= 3
       1757210.9      330815.485     1757772.914      330800.757
     1758268.938      330786.716
#Sta/Elev= 30
       0 1127.18    55.8 1111.66   150.8 1092.66   186.4 1082.26   257.5 1064.44
   293.3 1057.25     329 1052.32   340.8 1049.03   388.3 1029.93   431.5 1018.76
   447.7 1016.09   554.7 1006.69   562.2 1006.66   569.7  1007.4   578.4 1009.27
     614 1022.72   625.9 1024.48   697.1 1018.22     709 1018.69   720.9 1022.09
   732.8 1024.11   756.5 1022.82   768.4 1024.77   792.2 1036.09   839.7 1051.23
   851.5 1053.86   934.7  1058.8  1017.8 1065.46  1029.7 1067.37  1058.4 1077.04
#Mann= 3 , 0 , 0
       0      .1       0   554.7    .045       0   569.7      .1       0
Bank Sta=554.7,569.7
XS Rating Curve= 0 ,0
Exp/Cntr=0.3,0.1

Type RM Length L Ch R = 1 ,4263.6  ,360.319,362.554,361.095
XS GIS Cut Line= 3
     1757328.389      331191.796     1757838.495      331182.514
     1758339.692      331240.986
#Sta/Elev= 30
       0 1108.75    82.6 1090.32     152 1078.57   199.5 1065.43   223.3 1060.09
     247 1056.87   315.9 1051.42   332.9 1048.96   353.9 1043.43   365.8 1036.77
   377.6 1028.22   389.5  1022.5   401.4 1019.43   425.1 1016.97   448.9 1009.54
   460.8  1007.1     478 1005.48   502.7 1005.06   508.3  1004.9   517.7 1005.91
   544.1 1010.95   599.4 1013.68   699.5  1020.5   711.4 1022.91   735.4 1030.54
   807.1 1046.64     831 1050.46   878.8 1053.58   934.2 1054.83  1014.8 1058.61
#Mann= 3 , 0 , 0
       0      .1       0   502.7    .045       0   517.7      .1       0
Bank Sta=502.7,517.7
XS Rating Curve= 0 ,0
Exp/Cntr=0.3,0.1

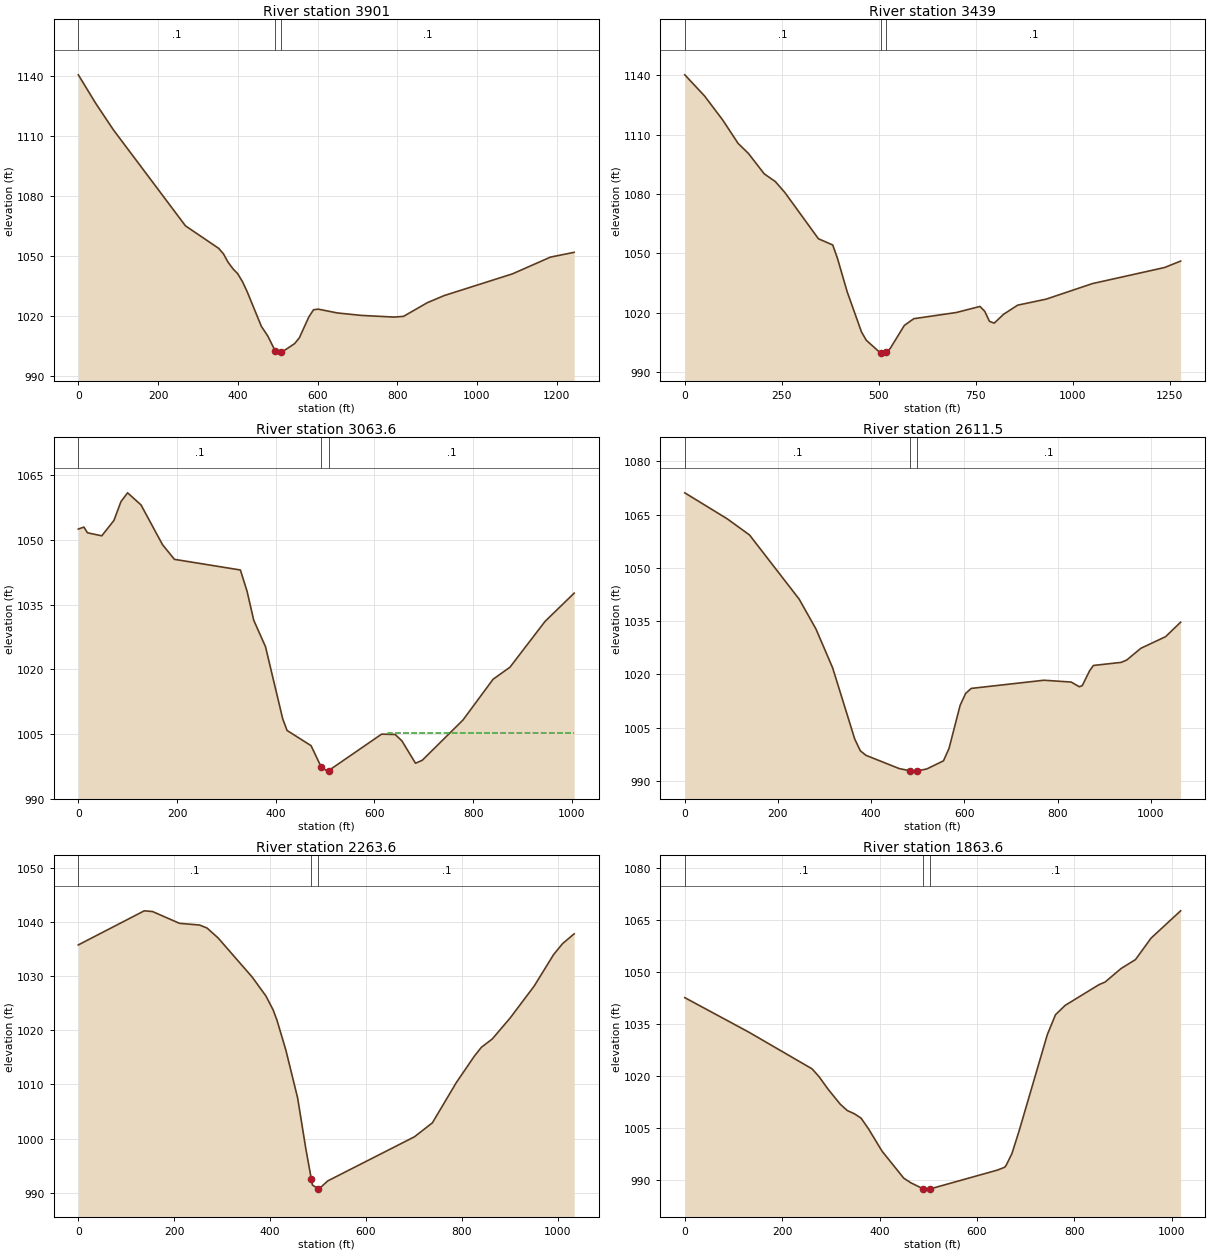
Type RM Length L Ch R = 1 ,3901    ,457.521,462.023,466.355
XS GIS Cut Line= 3
     1757283.706      331480.527     1757789.197      331519.297
     1758525.229      331552.216
#Sta/Elev= 30
       0 1140.47    43.9 1126.13    88.1 1112.93   268.7 1064.97     352 1053.72
     364 1050.97   375.6 1046.78   387.8 1043.51   399.7 1041.03   411.6 1037.13
   423.5 1032.05   459.2 1014.68   475.2  1009.9   494.4 1002.19   506.8 1001.32
   509.4 1001.66   542.5 1006.07   554.4 1008.98   578.2 1019.43     590 1023.01
   601.9 1023.31   649.5 1021.42   708.9  1020.2   792.1 1019.34   815.8 1019.71
   875.3 1026.53   917.9 1030.11  1089.2 1040.97  1184.3 1049.33  1243.7 1051.72
#Mann= 3 , 0 , 0
       0      .1       0   494.4    .045       0   509.4      .1       0
Bank Sta=494.4,509.4
XS Rating Curve= 0 ,0
Exp/Cntr=0.3,0.1

Type RM Length L Ch R = 1 ,3439    ,370.285,375.423,381.797
XS GIS Cut Line= 3
     1757184.666       331813.21     1757683.852      331954.602
     1758423.068      332127.848
#Sta/Elev= 30
       0 1140.19    50.8 1129.55    97.6  1117.4   137.4 1105.55     164 1100.48
   204.7 1090.17   233.5 1086.23     258 1080.72   344.4 1057.37   381.4 1054.21
   393.7 1047.37   418.4 1030.68   455.4  1010.3   467.8 1006.08   504.8  999.57
   519.8 1000.18   529.3 1001.87   565.9 1013.57   590.3 1016.97   699.4 1020.08
     761 1023.16   773.2 1020.69   785.4 1015.62   797.6 1014.73     822 1019.24
     858  1023.8   931.7 1026.86  1050.7  1034.7  1236.6 1042.82  1278.1 1046.08
#Mann= 3 , 0 , 0
       0      .1       0   504.8    .045       0   519.8      .1       0
Bank Sta=504.8,519.8
XS Rating Curve= 0 ,0
Exp/Cntr=0.3,0.1

Type RM Length L Ch R = 1 ,3063.6  ,462.038,452.098,442.277
XS GIS Cut Line= 3
     1757036.759      332020.375     1757474.415      332261.563
     1757910.911      332515.012
#Sta/Elev= 30
       0 1052.52    11.3 1052.99    18.5 1051.66    47.5 1050.96    72.1 1054.52
    86.3 1058.88    99.8 1060.93     127 1058.13   170.5 1048.91   194.7  1045.5
   328.3 1043.03   341.9 1038.07   355.4 1031.36   379.2 1025.23   414.1 1008.49
   422.9  1005.8   471.5 1002.28   492.2  997.29   504.6  996.37   507.2   996.5
   614.4 1004.95   641.9 1004.88   655.6 1003.38   683.1   998.2   696.8  998.89
   779.2 1008.22   840.3 1017.69   874.5 1020.48   945.4 1031.09  1004.5 1037.66
#Mann= 3 , 0 , 0
       0      .1       0   492.2    .045       0   507.2      .1       0
#XS Ineff= 2 , 0
                           627.1         1005.23
Permanent Ineff=
       F       F
Bank Sta=492.2,507.2
XS Rating Curve= 0 ,0
Exp/Cntr=0.3,0.1

Type RM Length L Ch R = 1 ,2611.5  ,361.268,347.902,339.134
XS GIS Cut Line= 3
     1756805.602      332639.665     1757299.756      332664.534
     1757867.082      332711.339
#Sta/Elev= 30
       0 1071.13    91.4 1063.78   138.9 1059.26   245.5 1041.17   281.6 1032.74
   317.3 1021.82   364.8 1001.74   376.7  998.47   388.6   997.2   459.9  993.47
   484.2  992.81   495.6  992.74   499.2   992.8   519.4  993.36   555.1  995.64
     567  999.13   590.9  1011.3   602.8 1014.65   614.7 1016.04   770.6 1018.34
   829.1 1017.83   846.7 1016.51     853 1016.83   868.7 1021.01   876.8  1022.5
   936.4 1023.37   948.3 1024.03   978.7 1027.34  1031.7 1030.61    1064 1034.69
#Mann= 3 , 0 , 0
       0      .1       0   484.2    .045       0   499.2      .1       0
Bank Sta=484.2,499.2
XS Rating Curve= 0 ,0
Exp/Cntr=0.3,0.1

Type RM Length L Ch R = 1 ,2263.6  ,401.419,400,392.405
XS GIS Cut Line= 3
     1756906.038      333241.301     1757328.606      332986.618
     1757842.925      332819.385
#Sta/Elev= 30
       0 1035.74   137.5 1042.03   154.8  1041.9   211.1 1039.72   252.7 1039.41
   268.4 1038.86   291.4 1037.04   362.4 1029.83   391.3 1026.31   406.4 1023.73
   414.3 1021.85   432.9 1016.32   457.5 1007.46   474.8  997.97   485.9  992.57
   488.3  991.41   500.9   990.7   501.4  990.66   520.3  992.18   701.1 1000.32
   738.5  1002.9   788.5 1010.34   825.9 1015.19   840.6 1016.83   863.4 1018.38
   900.8 1022.26   950.8 1028.14   991.3 1033.95  1010.2 1035.99  1034.2 1037.78
#Mann= 3 , 0 , 0
       0      .1       0   485.9    .045       0   500.9      .1       0
Bank Sta=485.9,500.9
XS Rating Curve= 0 ,0
Exp/Cntr=0.3,0.1

Type RM Length L Ch R = 1 ,1863.6  ,484.437,488.807,493.237
XS GIS Cut Line= 3
     1757109.713      333606.474      1757517.64      333322.405
     1757932.411      333006.623
#Sta/Elev= 30
       0 1042.69   131.3 1032.76   261.5 1022.15   275.9 1019.88   294.2 1016.31
   319.3 1011.96   333.8 1010.13   348.3 1009.21   362.1 1007.94   377.2 1004.89
   405.1  998.43   449.6  990.65     464  989.32   489.6  987.55     493  987.47
   504.6  987.56   642.1  992.96     657  993.78   659.9   994.3   671.9  997.71
   686.8 1004.33   744.6 1032.02   761.4 1037.77   781.3 1040.47     851 1046.46
   863.2 1047.18   895.7 1051.05   925.6 1053.66   957.7 1059.86  1018.4 1067.73
#Mann= 3 , 0 , 0
       0      .1       0   489.6    .045       0   504.6      .1       0
Bank Sta=489.6,504.6
XS Rating Curve= 0 ,0
Exp/Cntr=0.3,0.1

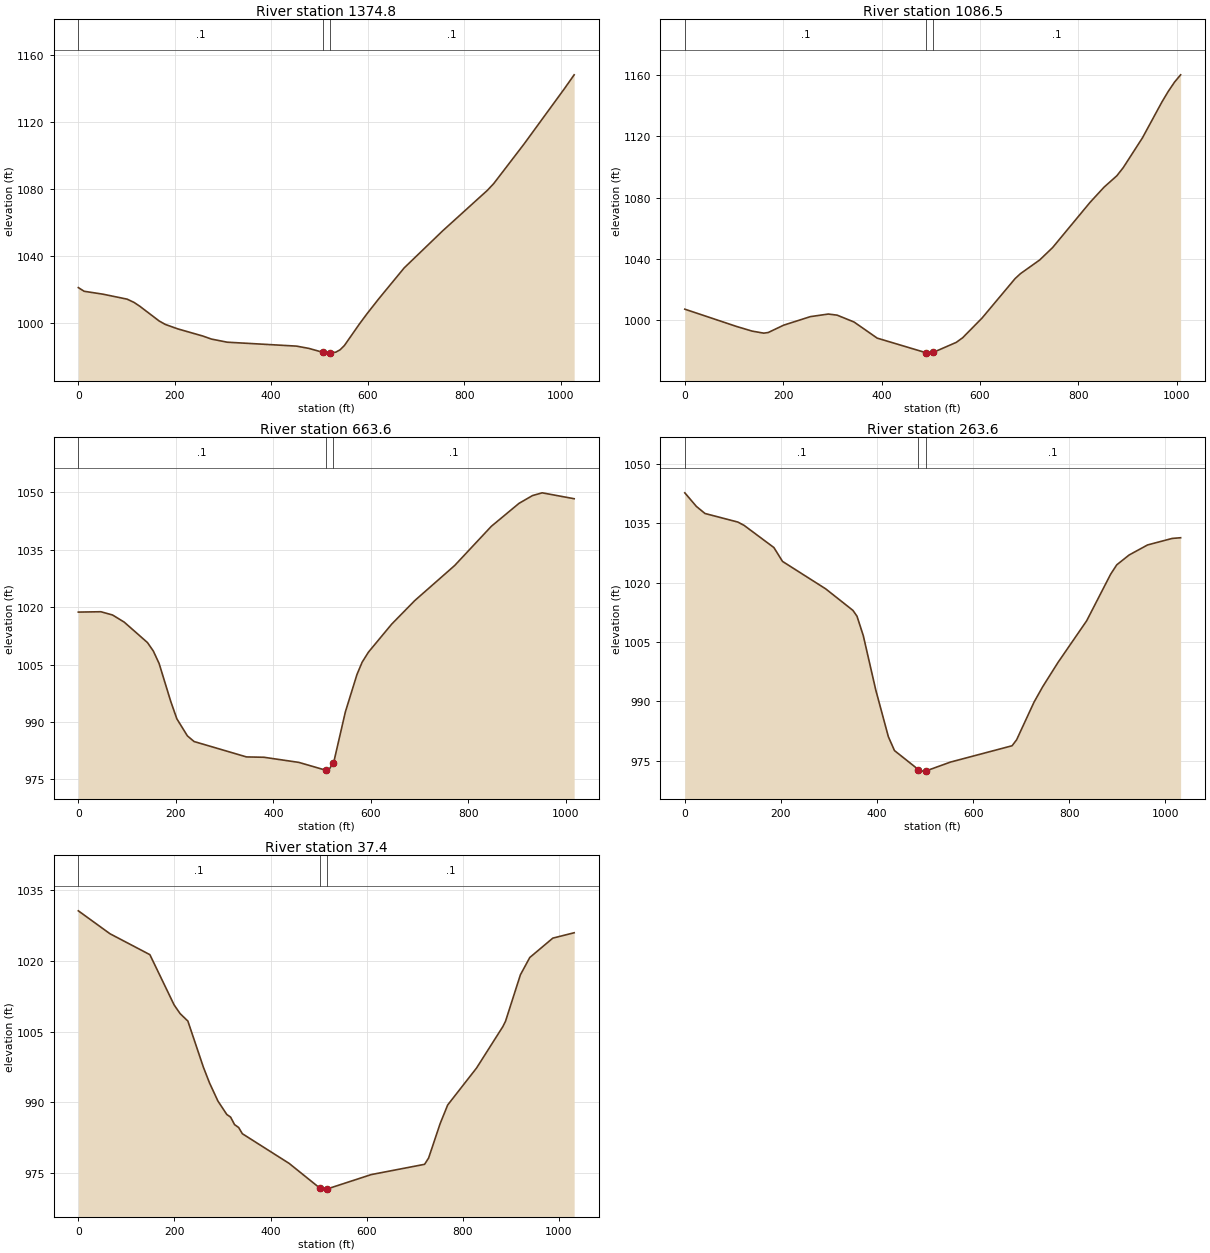
Type RM Length L Ch R = 1 ,1374.8  ,290.311,288.263,288.747
XS GIS Cut Line= 3
     1757396.309      333794.712      1757872.36      333587.475
     1758328.485      333361.837
#Sta/Elev= 30
       0 1021.37    12.1 1019.18    50.9 1017.46   101.2 1014.49   115.7 1012.51
   127.3 1010.29   167.5  1001.5   180.4  999.41   206.3  996.76   258.1   992.5
   276.1  990.68   308.7  988.83   452.4  986.49   478.3  985.11   507.5  982.75
   516.2  982.31   522.5  982.47   533.9  982.88   542.8   984.3   551.7  986.85
   583.3  999.87   598.1  1005.6     623 1014.72   675.7 1033.13   755.5 1055.22
   848.2 1079.37   861.4 1083.41   923.9 1106.86  1007.2 1139.68  1028.1 1148.22
#Mann= 3 , 0 , 0
       0      .1       0   507.5    .045       0   522.5      .1       0
Bank Sta=507.5,522.5
XS Rating Curve= 0 ,0
Exp/Cntr=0.3,0.1

Type RM Length L Ch R = 1 ,1086.5  ,413.932,422.93,432.471
XS GIS Cut Line= 3
     1757587.724      334059.684     1758024.462      333817.345
     1758487.104      333605.818
#Sta/Elev= 30
       0 1007.35   106.1  995.99     137  993.04   160.4  991.72   169.5  992.11
   201.1  996.93   255.4 1002.49   291.8 1004.17   309.7 1003.46   344.2  998.97
   391.2  988.47   490.3  978.97   499.5  978.69   505.3  979.19     552   985.7
   565.1  988.75   604.3 1001.51   671.6 1027.27   682.6 1030.52   721.7 1039.45
   747.9 1047.51   823.9 1076.94   852.3 1086.83   878.4  1094.3   891.5 1099.63
   930.6 1119.07   969.8 1142.23   982.8 1149.22   995.9 1155.44  1008.2 1160.15
#Mann= 3 , 0 , 0
       0      .1       0   490.3    .045       0   505.3      .1       0
Bank Sta=490.3,505.3
XS Rating Curve= 0 ,0
Exp/Cntr=0.3,0.1

Type RM Length L Ch R = 1 ,663.6   ,407.472,400,391.268
XS GIS Cut Line= 3
     1757658.198      334253.145     1758170.407      334197.292
     1758672.066      334189.997
#Sta/Elev= 30
       0  1018.7    46.3 1018.79    70.2 1017.94    94.1 1016.08   141.8 1010.74
   153.8 1008.54   165.7 1005.27   189.6  995.35   202.1  990.82   223.7  986.37
   237.4  984.89   344.9  980.87   380.7  980.78   452.4  979.44   507.7  977.39
   512.1  977.16   522.7  979.26     524  979.54   547.7  992.62   571.5 1002.39
   582.1 1005.61   595.2 1008.26   642.7 1015.55   690.2 1021.72   771.8 1030.85
   847.1  1041.1   903.9  1047.1   931.5 1049.13   951.4 1049.85    1017 1048.31
#Mann= 3 , 0 , 0
       0      .1       0   507.7    .045       0   522.7      .1       0
Bank Sta=507.7,522.7
XS Rating Curve= 0 ,0
Exp/Cntr=0.3,0.1

Type RM Length L Ch R = 1 ,263.6   ,232.672,226.167,219.04
XS GIS Cut Line= 3
     1757746.079      334779.358     1758195.527      334574.665
     1758693.939      334371.839
#Sta/Elev= 30
       0 1042.68    24.1 1039.25      42 1037.46   110.5 1035.29   123.6 1034.44
   185.4 1028.86   203.4 1025.35   293.2 1018.42   349.9 1012.98   358.4 1011.51
   371.5  1006.6   397.6  992.81   423.7  981.06   436.4  977.56   486.4  972.73
   490.2  972.36   501.4  972.38   553.1  974.65   681.2  978.77   690.6  980.27
     727  989.82     745   993.7   776.5  999.77   836.4 1010.34   886.3 1022.11
   899.1 1024.49   924.8 1026.97   963.2 1029.51  1014.5 1031.16    1032 1031.33
#Mann= 3 , 0 , 0
       0      .1       0   486.4    .045       0   501.4      .1       0
Bank Sta=486.4,501.4
XS Rating Curve= 0 ,0
Exp/Cntr=0.3,0.1

Type RM Length L Ch R = 1 ,37.4    ,45.021,37.397,29.474
XS GIS Cut Line= 3
     1757929.009      335117.055     1758290.787      334780.873
     1758699.612      334430.994
#Sta/Elev= 30
       0 1030.67    65.9  1025.8   148.9 1021.36   199.3  1010.7   211.8 1008.84
     228 1007.25   260.4  997.42   273.1   994.1   290.5  990.27     309  987.41
   316.9  986.85   325.2  985.25   333.7  984.64   341.4  983.32   438.7  977.02
   502.7  971.77   510.2  971.55   517.7  971.58   609.7  974.64   720.7  976.82
   729.1  978.17   753.2  985.51   768.8  989.43   828.8  997.27   883.6 1006.08
   889.1  1007.2   920.1 1017.07   939.6 1020.75   987.6 1024.87    1032 1026.01
#Mann= 3 , 0 , 0
       0      .1       0   502.7    .045       0   517.7      .1       0
Bank Sta=502.7,517.7
XS Rating Curve= 0 ,0
Exp/Cntr=0.3,0.1

Chan Stop Cuts=-1
Use User Specified Reach Order=0